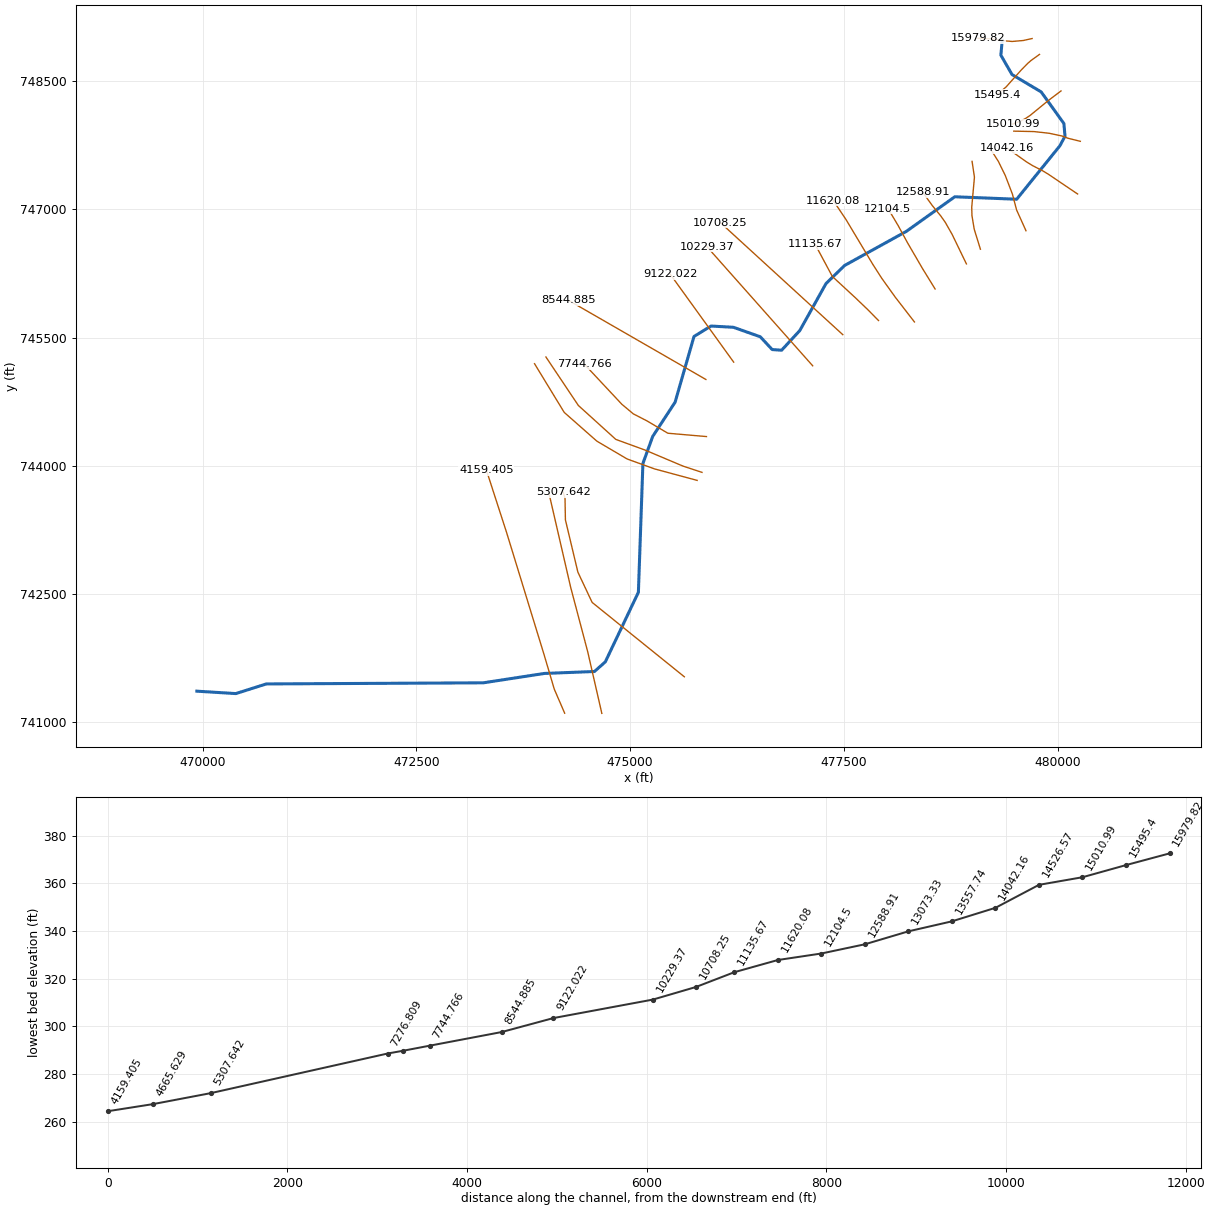
--- 2498_ras.prj (project) ---

Proj Title=2498
Current Plan=p01
Default Exp/Contr=0.3,0.1
English Units
Geom File=g01
Flow File=f01
Plan File=p01
Y Axis Title=Elevation
X Axis Title(PF)=Main Channel Distance
X Axis Title(XS)=Station
BEGIN DESCRIPTION:
RFD model 2498 exported to HEC-RAS
END DESCRIPTION:

--- 2498_ras.p01 (plan) ---

Plan Title=Plan 01
Program Version=4.10
Short Identifier=Plan 01
Geom File=g01
Flow File=f01
Subcritical Flow
Calc Critical at every XS
Secant Critical Depth

--- 2498_ras.f01 (steady flow) ---

Flow Title=Flow 01
Program Version=5.01
Number of Profiles= 6
Profile Names=10yr,25yr,50yr,100yr,100plus,500yr
River Rch & RM=2498,21,15979.82
10611.5415718.46   1747319554.5131060.6624938.16
River Rch & RM=2498,21, 15495.4
10621.0615737.6117501.0919592.6731121.2725005.49
River Rch & RM=2498,21,15010.99
 10626.715748.9517517.7319615.29 31157.225045.44
River Rch & RM=2498,21,14526.57
10639.7415775.17 17556.2 19667.631240.2925137.86
River Rch & RM=2498,21,14042.16
 10654.515804.8817599.8319726.9431334.5525242.83
River Rch & RM=2498,21,13557.74
10674.0115844.1717657.5719805.5331459.3825382.02
River Rch & RM=2498,21,13073.33
10698.3815893.2717729.7819903.8931615.6325556.56
River Rch & RM=2498,21,12588.91
 10716.315929.4117782.9819976.4231730.8325685.45
River Rch & RM=2498,21, 12104.5
10721.5215939.95 17798.519997.5831764.4425723.09
River Rch & RM=2498,21,11620.08
10743.4615984.2217863.75 20086.631905.8425881.62
River Rch & RM=2498,21,11135.67
10765.78 16029.317930.2320177.3832050.0426043.54
River Rch & RM=2498,21,10708.25
10769.0716035.9517940.0520190.7932071.3526067.49
River Rch & RM=2498,21,10229.37
10785.3516068.8517988.6120257.1632176.7626186.07
River Rch & RM=2498,21,9122.022
11464.1917456.5220065.4623130.2436740.4131458.78
River Rch & RM=2498,21,8544.885
11540.3917614.1820304.8523465.6537273.1632091.48
River Rch & RM=2498,21,7744.766
11569.5417674.5620396.7223594.5937477.9832335.64
River Rch & RM=2498,21,7443.203
11573.32 17682.420408.6623611.3637504.6132367.44
River Rch & RM=2498,21,7276.809
 11574.817685.4820413.3523617.9437515.0832379.93
River Rch & RM=2498,21,5307.642
11591.6617720.44 20466.623692.7437633.8932521.86
Boundary for River Rch & Prof#=2498,21,1
Up Type= 0
Dn Type= 2
Boundary for River Rch & Prof#=2498,21,2
Up Type= 0
Dn Type= 2
Boundary for River Rch & Prof#=2498,21,2
Up Type= 0
Dn Type= 2
Boundary for River Rch & Prof#=2498,21,2
Up Type= 0
Dn Type= 2
Boundary for River Rch & Prof#=2498,21,2
Up Type= 0
Dn Type= 2
Boundary for River Rch & Prof#=2498,21,2
Up Type= 0
Dn Type= 2

--- 2498_ras.g01 (geometry) ---

Geom Title=2498
Program Version=4.10

River Reach=2498,21
Reach XY= 30
479352.270444989748976.935301304479336.645444989748802.456134617
479466.853778452748575.893634617479807.999611676748372.768634632
480073.624611765748002.976967946480086.645444989747854.539467946
480026.749611735747742.560301304479521.541278332747117.560301289
478797.582944989747146.206134632478232.478778452746742.560301304
477509.114037156 746342.76806581477291.753026962746131.656839013
476984.656246036745581.229963318476772.308756828745351.795700163
476661.891755998745359.434488639476523.003174275745508.740292922
476209.114236593745619.851261586475945.919712573745634.434735924
475747.308718443745512.212376162475526.648789495744743.774597466
475265.031293333744343.923705205 475150.10073784744027.257038489
 475097.21011278742520.763983011474710.522521645741706.966187328
474583.569396645741594.118965089473997.631896645741571.332506806
473282.571132749741461.740492895470745.678771645741448.719659552
470388.690924406741335.872437343469932.961757749 741364.08424288

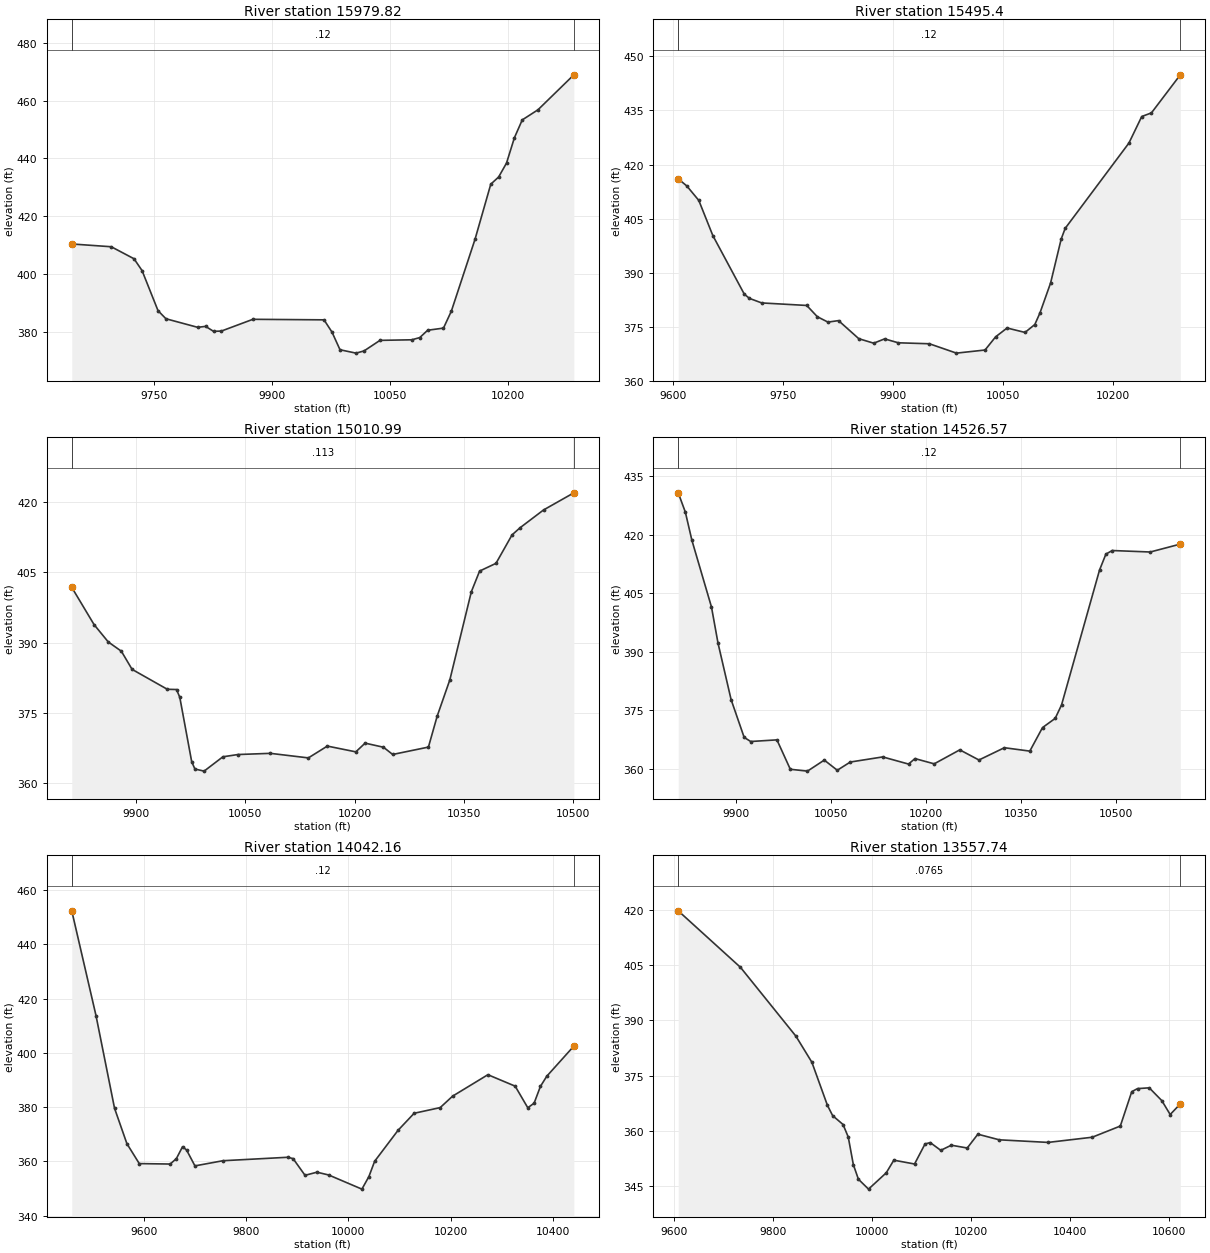
Type RM Length L Ch R = 1 ,15979.82,484.414900,484.414900,484.414900
XS GIS Cut Line= 6
 479702.04810822748997.052368104479599.279950142748974.086090744
 479467.72967124748962.672243521479382.956044197748970.103041783
 479238.49909848748992.697642088479069.461095642748999.303292781
#Sta/Elev= 30
9645.881410.40179696.086409.44039724.985405.28639735.182401.20879755.525387.3109
9765.603384.50869805.915381.54739815.993381.87679826.071380.15939836.103380.2589
9876.122384.32429966.494384.13949976.651379.89229986.828373.783610007.17372.6155
10017.32373.369210037.63377.032210078.12377.232910088.18377.994110098.24380.5371
10118.35381.276110128.38387.165610158.45 412.03610178.47431.096210188.47433.5948
10198.48 438.41410208.48447.162810218.48453.354210238.49456.862110284.05468.9568
#Mann= 3 , 0 , 0
9645.881    0.12       09645.881    0.12       010284.05    0.12       0
#XS Ineff= 2 , 0
       0                               0
Bank Sta=9645.881,10284.05
Exp/Cntr=0.3,0.1

Type RM Length L Ch R = 1 , 15495.4,484.414900,484.414900,484.414900
XS GIS Cut Line= 6
479788.515950203748811.404961318479691.042272359748741.304742008
479655.506507516748710.857956737479578.310257167748632.995078817
 479399.82833758748432.976962686479293.997008776748340.666645655
#Sta/Elev= 30
9606.779416.0308 9618.52414.04559634.838 410.0499653.983400.31029696.969384.0525
9704.043  382.88 9720.73381.62839782.167 380.9299796.636377.80799811.105376.3143
9825.574376.7272 9853.21371.71719873.596370.46969888.435371.66199907.173370.5776
9949.565370.31059986.517367.714110025.55368.578910039.92372.221410055.62374.6787
 10080.1373.451710093.49375.6442 10100.5378.8582   10115387.150710129.49399.3549
10134.89  402.2910221.95425.953310239.42433.303310252.67434.311110292.06 444.858
#Mann= 3 , 0 , 0
9606.779    0.12       09606.779    0.12       010292.06    0.12       0
#XS Ineff= 2 , 0
       0                               0
Bank Sta=9606.779,10292.06
Exp/Cntr=0.3,0.1

Type RM Length L Ch R = 1 ,15010.99,484.414900,484.414900,484.414900
XS GIS Cut Line= 6
480039.977794886748384.157708436  479890.5587928748271.170439258
479678.142190874 748097.17555806479630.513626397748065.417861804
479569.733315557748032.220032096479475.600034029747995.899435028
#Sta/Elev= 30
9811.643401.76399842.263393.83299861.744390.13859879.729388.16269894.491384.2939
9942.875380.05199955.504380.00259959.983378.34879976.357364.61059980.762363.0701
9993.391362.619110019.17365.671310039.94366.155810084.38366.406910136.54365.4356
10162.62367.954210201.74366.723910214.49368.583510239.73367.707410252.35366.1669
10301.44367.739610313.46 374.32710330.87382.070210360.38400.833210371.73405.2325
10394.22406.881110416.27412.938910427.21414.453410459.53 418.25110501.15421.9015
#Mann= 3 , 0 , 0
9811.643   0.113       09811.643   0.113       010501.15   0.113       0
#XS Ineff= 2 , 0
       0                               0
Bank Sta=9811.643,10501.15
Exp/Cntr=0.3,0.1

Type RM Length L Ch R = 1 ,14526.57,484.414800,484.414800,484.414800
XS GIS Cut Line= 6
480266.019394368747794.977992892 480122.10072729747830.639034852
480049.668529212747857.572365135479900.292939812747889.211114198
479724.807486087747908.842968121479487.563705623747913.862829799
#Sta/Elev= 30
9808.762430.68059820.027425.7164 9830.28418.55759861.224401.44889871.538 392.202
9892.167377.75559912.796368.0712 9923.11367.0105 9964.53367.43079985.647359.9023
10012.73359.426310039.26362.251710059.78359.6518 10080.3361.753910131.49363.0618
10172.21361.2356 10182.4362.635410212.73361.293810253.12364.872710283.36362.2769
 10323.5365.420710363.64 364.55110383.66 370.56910403.68372.927610413.69376.3585
10473.71410.923410483.71414.989210493.71 415.90710553.72415.530610601.16417.5552
#Mann= 3 , 0 , 0
9808.762    0.12       09808.762    0.12       010601.16    0.12       0
#XS Ineff= 2 , 0
       09908.176                       0
Bank Sta=9808.762,10601.16
Exp/Cntr=0.3,0.1

Type RM Length L Ch R = 1 ,14042.16,484.414900,484.414900,484.414900
XS GIS Cut Line= 6
480234.171603918747178.676976144479888.693861574747412.056038231
479821.613222122747452.278908774479709.841472417 747509.40190345
 479632.87439695 747556.62746802 479412.10205119747713.721045458
#Sta/Elev= 30
9459.287452.4098 9506.66413.79419542.941379.60339567.128366.54779591.315359.2016
9651.783359.04179663.877361.04649675.971365.43879683.911364.18859700.158358.3607
9755.038 360.2639881.937361.53799892.179 361.0349915.499354.88199938.819356.0343
9961.834354.999510026.72349.788810040.39354.408910051.64360.062810097.36371.4629
 10128.9377.762710179.82379.8502 10204.1384.070910273.13391.978310326.45387.7591
10351.16 379.79210363.52381.482510375.87 387.66810388.23391.406910441.23402.5266
#Mann= 3 , 0 , 0
9459.287    0.12       09459.287    0.12       010441.23    0.12       0
#XS Ineff= 2 , 0
       0 9720.75                       0
Bank Sta=9459.287,10441.23
Exp/Cntr=0.3,0.1

Type RM Length L Ch R = 1 ,13557.74,484.414900,484.414900,484.414900
XS GIS Cut Line= 6
479630.242923528746749.065193042479520.039628446 746993.17062749
479472.014663279747176.461414337 479388.05921641747395.468876794
479307.432798803 747559.78667751479233.115381079747676.870848673
#Sta/Elev= 30
 9608.49 419.7899734.247404.42149846.174385.71379878.432378.62149909.925366.8842
9920.423364.09739941.419361.68429951.917358.29299962.241350.76649972.451346.8116
9992.871344.114710028.68348.549510044.01 351.98710085.87350.946610107.04356.3964
10117.62356.768210138.78354.664310160.18356.057410192.32355.295310213.75  359.05
10256.98357.523310355.62356.817910444.71358.223910501.54361.267310524.64370.6152
10536.29371.443510559.98371.662110585.39 368.17610602.25 364.40310622.73367.2857
#Mann= 3 , 0 , 0
 9608.49  0.0765       0 9608.49  0.0765       010622.73  0.0765       0
#XS Ineff= 2 , 0
       0                10303.77       0
Bank Sta=9608.49,10622.73
Exp/Cntr=0.3,0.1

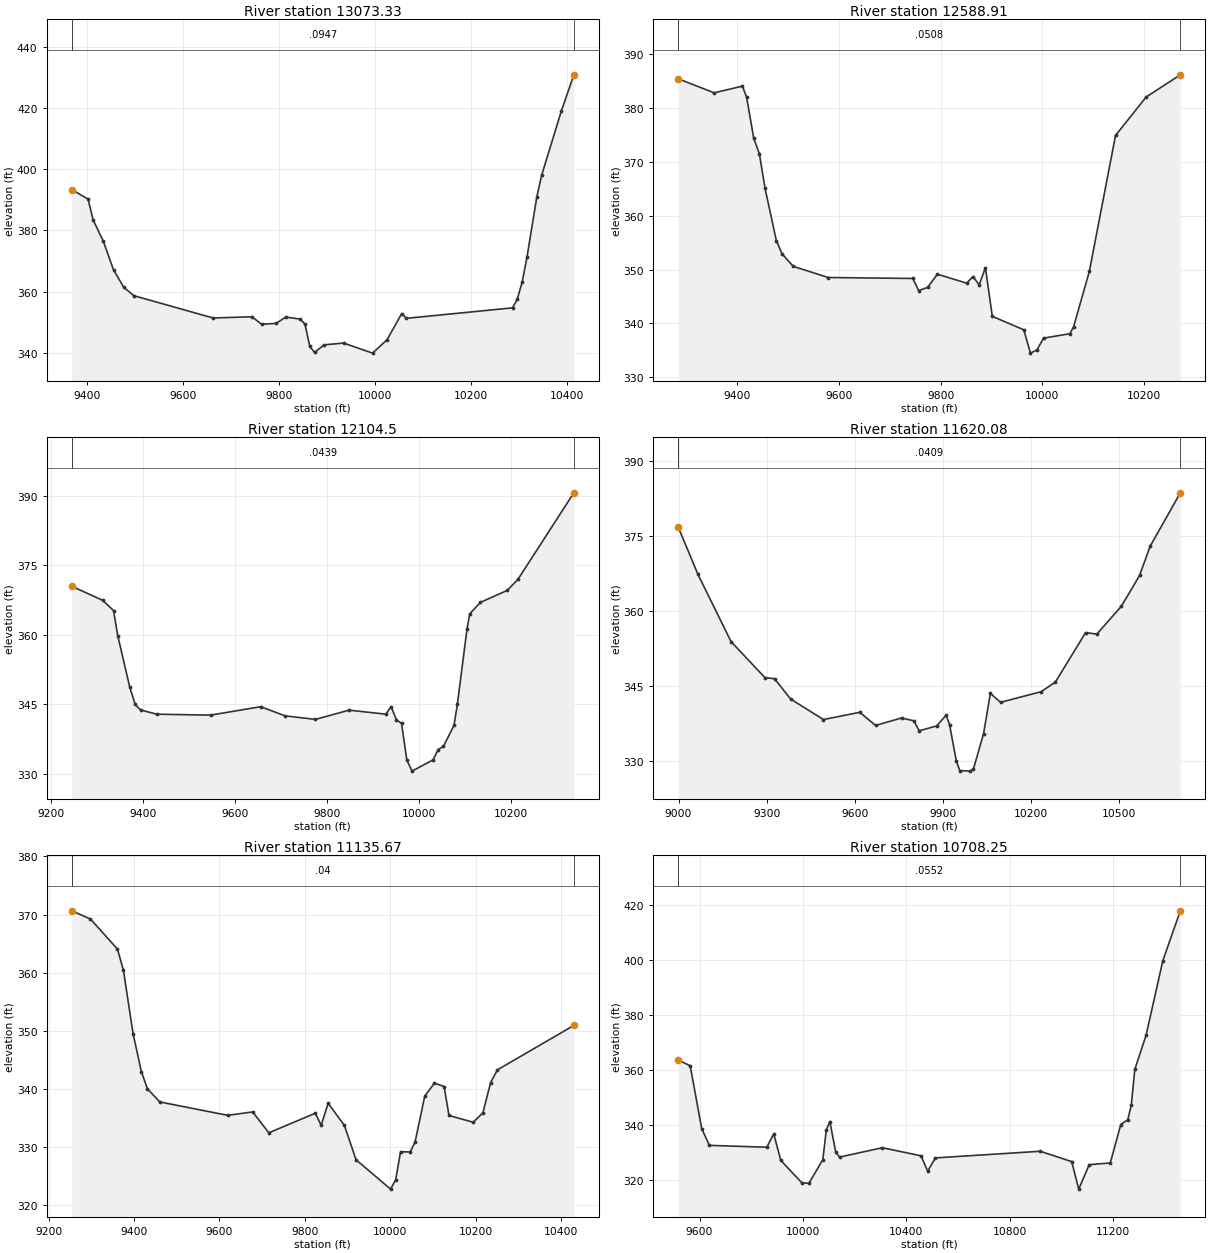
Type RM Length L Ch R = 1 ,13073.33,484.414900,484.414900,484.414900
XS GIS Cut Line= 6
  479097.2223984746532.995503351479024.929888248746767.003167555
478998.626199901746925.284620181478995.845090687747023.067482591
479027.504338354747375.732692242478999.879075661747560.340891386
#Sta/Elev= 30
9368.313393.34589402.257390.21099412.863383.40669434.074376.41499455.286367.1001
 9476.28  361.499497.187358.69319662.431351.40169743.478351.79489763.607349.3388
9793.704349.63499813.734351.6987 9843.76351.0349 9853.76349.3855 9863.76342.0987
9873.766340.15259893.825342.62419933.944343.21319994.474339.919210024.72344.3187
10054.97352.811110065.05351.290610285.73354.704210295.81 357.59710305.88 363.163
10315.96371.353910336.19390.7864 10346.4398.054610387.27 418.936 10413.4430.8234
#Mann= 3 , 0 , 0
9368.313  0.0947       09368.313  0.0947       0 10413.4  0.0947       0
#XS Ineff= 2 , 0
       09666.212        10145.27       0
Bank Sta=9368.313,10413.4
Exp/Cntr=0.3,0.1

Type RM Length L Ch R = 1 ,12588.91,484.414900,484.414900,484.414900
XS GIS Cut Line= 6
478933.590773702746361.423578322478765.587871373746708.108734995
478686.365086257746847.391979069478634.355341077746921.197212353
478533.227361381747045.106757954478421.809349928747200.363931475
#Sta/Elev= 30
9284.207385.44439354.855382.84189410.417384.09089418.562382.02419432.641374.3975
9443.754371.48729454.866365.08379477.091 355.3829488.203 352.9449510.428 350.603
9579.079348.53369745.376348.35819756.885346.09789774.288346.70079793.654 349.147
9851.283347.48399863.516348.7138 9875.75347.16999887.983350.36639901.552341.3236
9963.543 338.8139976.415334.48939989.287335.072710002.19337.272910053.95338.0959
10061.42339.391110092.33349.673410143.73374.916410203.83 382.05510271.11386.1868
#Mann= 3 , 0 , 0
9284.207  0.0508       09284.207  0.0508       010271.11  0.0508       0
#XS Ineff= 2 , 0
       09635.437                       0
Bank Sta=9284.207,10271.11
Exp/Cntr=0.3,0.1

Type RM Length L Ch R = 1 , 12104.5,484.414900,484.414900,484.414900
XS GIS Cut Line= 6
478567.406578004746067.690334514478424.550025403746299.548071265
478246.180497557746605.832158506478134.139949918 746811.29106757
478061.229157507746933.901629418478015.223523345747008.856114624
#Sta/Elev= 30
9245.306 370.449 9312.62367.41239336.112365.21479345.211 359.8279371.349348.7217
9383.095344.99439394.841343.79639430.078 342.8859547.094 342.6829655.843344.4982
9709.104342.52379775.068341.7631 9847.97343.75819928.038342.88479939.419344.5086
9950.801341.70549962.182340.87929973.564333.04119984.945330.6175 10030.5333.0337
10041.91335.276110053.31335.963310076.12340.454210083.51344.984110104.31361.1381
10110.42 364.52210133.68366.980310191.86369.552810215.13371.9291 10336.7390.5789
#Mann= 3 , 0 , 0
9245.306  0.0439       09245.306  0.0439       0 10336.7  0.0439       0
#XS Ineff= 2 , 0
       09717.552                       0
Bank Sta=9245.306,10336.7
Exp/Cntr=0.3,0.1

Type RM Length L Ch R = 1 ,11620.08,484.414900,484.414900,484.414900
XS GIS Cut Line= 6
478325.840410918745682.180906445 478101.39721331745972.287437499
477944.078318238746192.071087912477839.499156058746354.970671281
477526.224788338746878.526172429477376.919984251747101.034740776
#Sta/Elev= 30
8999.025376.71479066.145367.25949178.734353.80969293.723 346.6179326.953346.3673
9381.581342.31819493.133338.21049616.992339.65819670.764337.03639758.955338.5196
9800.526337.96199819.362335.95749878.171336.92679910.895339.06469922.486337.1965
9945.668329.86769957.259328.00419992.033327.887810003.57328.265110038.28335.3992
10061.41343.443610096.12341.656510234.17343.7849 10282.6345.709210385.48355.5985
10423.97355.318210507.57360.901610569.23367.040710605.04372.867410707.88383.5782
#Mann= 3 , 0 , 0
8999.025  0.0409       08999.025  0.0409       010707.88  0.0409       0
#XS Ineff= 2 , 0
       09859.348           10071       0
Bank Sta=8999.025,10707.88
Exp/Cntr=0.3,0.1

Type RM Length L Ch R = 1 ,11135.67,427.421500,427.421500,427.421500
XS GIS Cut Line= 6
477905.665687472745698.676591948477783.098747224745823.390121073
477633.006529778745967.105082676477374.097114444746206.361326754
477365.669679433746214.479730666477162.829218656746592.786120415
#Sta/Elev= 30
9254.106 370.6499297.855369.24029361.118364.07439375.139360.41399397.721349.5071
9417.202342.98399431.294340.04279460.212337.77739619.265335.4692 9677.87336.0546
9715.749332.46399824.677335.83299838.293333.74949854.683337.55049892.757333.7368
9919.989327.8316   10001322.775510012.94324.388910024.28329.202110046.98329.1701
10058.32330.889510081.02338.783510103.71 341.009 10126.4340.424710137.75335.4469
10194.49334.276510217.18335.8964 10235.2341.071110251.22343.293410430.26350.9344
#Mann= 3 , 0 , 0
9254.106    0.04       09254.106    0.04       010430.26    0.04       0
#XS Ineff= 2 , 0
       09866.578        10110.89       0
Bank Sta=9254.106,10430.26
Exp/Cntr=0.3,0.1

Type RM Length L Ch R = 1 ,10708.25,478.877400,478.877400,478.877400
XS GIS Cut Line= 2
477487.481996447745533.758342624 476055.19032979746844.522231489
#Sta/Elev= 30
9517.591363.53189563.867361.45719608.303338.60879637.928332.49439859.841331.8106
9886.952336.67429914.063327.03299995.396318.892710023.05318.692610076.73327.2974
10090.28338.146210103.84341.162410126.73330.021310141.54328.235110307.17331.6292
10456.28328.692610482.23323.113410511.85327.929310917.17330.343311039.17326.5801
11066.28316.568211106.94325.467711188.28326.088611228.94340.074511256.05341.8502
11269.61347.122211283.16360.149511326.52372.477911391.61399.701511459.13417.8384
#Mann= 3 , 0 , 0
9517.591  0.0552       09517.591  0.0552       011459.13  0.0552       0
#XS Ineff= 2 , 0
       09897.256        10114.96       0
Bank Sta=9517.591,11459.13
Exp/Cntr=0.3,0.1

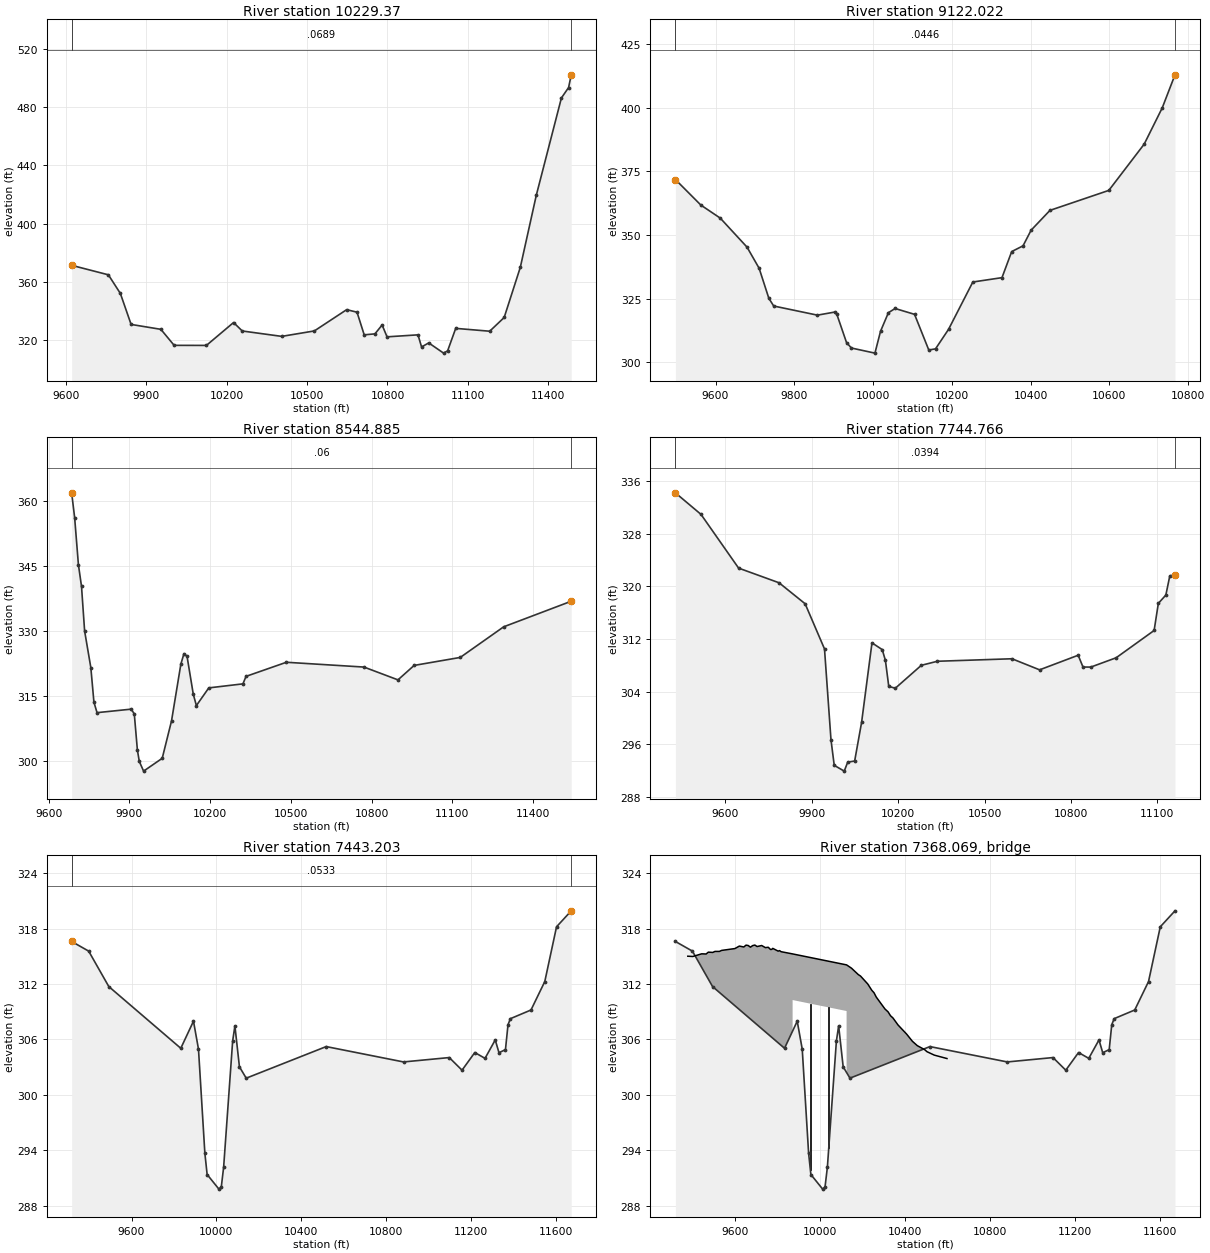
Type RM Length L Ch R = 1 ,10229.37,1107.348700,1107.348700,1107.348700
XS GIS Cut Line= 2
477135.919496477745169.175009295 475898.94032979746562.404175952
#Sta/Elev= 30
9622.234371.50869759.176 365.0069803.868352.24549843.986330.9687 9954.98 327.611
10004.46316.622610124.81316.576910226.09332.279310258.54326.468610405.64322.7752
10527.33326.511210647.82341.100210686.46339.362110713.21323.830310753.26324.4983
10780.07 330.59110798.44322.4585 10913.8323.828210927.17315.524110953.92318.2916
11009.31311.287211024.37312.879211054.49328.265811181.25 326.31211235.24335.7251
11295.48370.1825 11355.1419.6258 11448.7 486.31411475.45493.447211485.35502.1701
#Mann= 3 , 0 , 0
9622.234  0.0689       09622.234  0.0689       011485.35  0.0689       0
#XS Ineff= 2 , 0
       0                10242.77       0
Bank Sta=9622.234,11485.35
Exp/Cntr=0.3,0.1

Type RM Length L Ch R = 1 ,9122.022,577.136900,577.136900,577.136900
XS GIS Cut Line= 2
 476211.44032979745212.577787057 475469.25282979746241.223620385
#Sta/Elev= 30
9498.007371.7678 9562.65361.72519611.974356.5881 9679.92 345.1879710.624336.8796
9735.287325.07359747.618 322.0469858.599318.45429902.098 319.6559907.924318.7806
9932.586307.65939944.917305.537910004.64303.5293 10018.9312.133110038.82319.4199
 10055.9321.070410105.22318.772410141.37304.756310158.46305.207710191.54312.8777
 10253.2331.481210327.19333.194910351.85343.440310380.64345.696210401.17351.8465
   10449 359.63510598.47367.488210688.27385.678510734.12399.930210766.45 412.912
#Mann= 3 , 0 , 0
9498.007  0.0446       09498.007  0.0446       010766.45  0.0446       0
#XS Ineff= 2 , 0
       0                10118.85       0
Bank Sta=9498.007,10766.45
Exp/Cntr=0.3,0.1

Type RM Length L Ch R = 1 ,8544.885,800.119700,800.119700,800.119700
XS GIS Cut Line= 2
475886.787552029745009.452787057474277.412551999  745936.5361204
#Sta/Elev= 30
9685.182361.78789696.295356.09659710.325345.24079721.866340.21799733.407329.9447
9756.488321.52369768.028313.54399779.569311.13079906.514311.93789918.055310.8497
9929.595 302.5089936.701299.88899952.676297.656710021.92300.612710056.54309.2473
10091.16322.2991 10102.7324.738510114.24324.097610137.32315.403810148.87312.7565
10195.03 316.83810321.97317.766310333.51 319.49310483.54 322.74210772.05321.6354
10898.32 318.68510958.43322.016811129.81323.854911291.38330.914411542.48336.8081
#Mann= 3 , 0 , 0
9685.182    0.06       09685.182    0.06       011542.48    0.06       0
#XS Ineff= 2 , 0
       0                10109.48       0
Bank Sta=9685.182,11542.48
Exp/Cntr=0.3,0.1

Type RM Length L Ch R = 1 ,7744.766,301.563100,301.563100,301.563100
XS GIS Cut Line= 6
 475893.51529935 744341.77148807475442.126410484 744380.83398807
475196.218448013744525.896452561475037.881159782744607.356704712
474903.931966037744719.375654727474465.563910514745188.125654712
#Sta/Elev= 30
9427.392334.22539516.238330.95089646.724 322.7889787.247320.55569877.583317.3687
9944.774310.50799967.287296.68969978.544292.821410013.24291.941610025.29293.3063
 10049.4293.4784 10073.5299.356610109.51 311.43110145.11310.403710156.11308.7632
10167.73304.8132 10190.5304.537210280.73308.0188 10336.5308.633810595.22309.0139
10691.06307.331710824.94309.547910841.66307.758310868.86307.750310956.71309.1647
11088.47313.312211103.11  317.4311129.18318.695211142.88321.612411160.85321.7113
#Mann= 3 , 0 , 0
9427.392  0.0394       09427.392  0.0394       011160.85  0.0394       0
#XS Ineff= 2 , 0
       09905.504        10116.58       0
Bank Sta=9427.392,11160.85
Exp/Cntr=0.3,0.1

Type RM Length L Ch R = 1 ,7443.203,166.394000,166.394000,166.394000
XS GIS Cut Line= 6
 475841.21495226743923.151696384475619.860785484 743996.06836307
475170.336472154744185.772509739474833.402452141 744308.56836307
 474395.00000003744705.683657005474015.679651201  745272.5585251
#Sta/Elev= 30
9317.961316.61879398.205315.57119492.962311.73259832.102305.04199891.895307.9801
9915.465304.95029945.485293.67499956.204291.361910011.74289.777710022.85290.0027
10033.96292.161310076.41305.8281   10087307.472910108.32303.035710140.29301.8021
10517.05305.225810881.35303.562211096.76304.036411156.92302.667811217.08304.5824
11265.21303.950311313.34305.948111330.94304.564111361.47304.8941 11373.5307.5939
11384.89308.252911481.79309.192411546.72312.273511602.12318.207911671.37319.9389
#Mann= 3 , 0 , 0
9317.961  0.0533       09317.961  0.0533       011671.37  0.0533       0
#XS Ineff= 2 , 0
       09872.258        10093.84       0
Bank Sta=9317.961,11671.37
Exp/Cntr=0.3,0.1

Type RM Length L Ch R = 3 ,7368.069,,,
BEGIN DESCRIPTION:
END DESCRIPTION:
Bridge Culvert--1,0,-1,-1, 0
Deck Dist Width WeirC Skew NumUp NumDn MinLoCord MaxHiCord MaxSubmerge Is_Ogee
54.325650,57.742700,2.6,0, 50, 50, , , 0.95, 0, 0,0,,
 9376.49 9399.99 9441.75 9462.63 9473.08 9493.96 9504.40 9525.28 9535.72 9598.36
 9619.24 9640.23 9650.56 9661.00 9671.44 9681.88 9692.32 9702.76 9724.50 9741.93
 9755.43 9766.03 9772.07 9776.63 9802.21 9808.43 9815.91 9870.09 9870.0910124.35
10124.3510147.6510179.4510190.0510224.1710243.0510253.6510264.2510305.2510319.83
10331.2910342.7510366.6710407.6210434.4310457.3510491.7310503.1910537.5710597.29
  315.02  314.99  315.28  315.26  315.46  315.43  315.54  315.54  315.65  315.85
  316.12  316.02  316.22  316.18  316.00  316.17  316.23  316.07  316.18  315.95
  315.99  315.75  315.76  315.87  315.57  315.63  315.51  315.27  315.27  314.08
  314.08  313.72  313.03  312.87  312.01  311.33  311.06  310.59  309.30  308.99
  308.57  308.33  307.57  306.57  305.80  305.33  304.90  304.67  304.30  303.93
 -684.98 -685.01 -684.72 -684.74 -684.54 -684.57 -684.46 -684.46 -684.35 -684.15
 -683.88 -683.98 -683.78 -683.82 -684.00 -683.83 -683.77 -683.93 -683.82 -684.05
 -684.01 -684.25 -684.24 -684.13 -684.43 -684.37 -684.49 -684.73  310.27  309.08
 -685.92 -686.28 -686.97 -687.13 -687.99 -688.67 -688.94 -689.41 -690.70 -691.01
 -691.43 -691.67 -692.43 -693.43 -694.20 -694.67 -695.10 -695.33 -695.70 -696.07
 9376.49 9399.99 9441.75 9462.63 9473.08 9493.96 9504.40 9525.28 9535.72 9598.36
 9619.24 9640.23 9650.56 9661.00 9671.44 9681.88 9692.32 9702.76 9724.50 9741.93
 9755.43 9766.03 9772.07 9776.63 9802.21 9808.43 9815.91 9843.18 9843.1810097.45
10097.4510118.7510133.7510194.0310224.1710243.0510253.6510264.2510305.2510319.83
10331.2910342.7510366.6710407.6210434.4310457.3510491.7310503.1910537.5710597.29
  315.02  314.99  315.28  315.26  315.46  315.43  315.54  315.54  315.65  315.85
  316.12  316.02  316.22  316.18  316.00  316.17  316.23  316.07  316.18  315.95
  315.99  315.75  315.76  315.87  315.57  315.63  315.51  315.39  315.39  314.23
  314.23  314.14  313.97  312.78  312.01  311.33  311.06  310.59  309.30  308.99
  308.57  308.33  307.57  306.57  305.80  305.33  304.90  304.67  304.30  303.93
 -684.98 -685.01 -684.72 -684.74 -684.54 -684.57 -684.46 -684.46 -684.35 -684.15
 -683.88 -683.98 -683.78 -683.82 -684.00 -683.83 -683.77 -683.93 -683.82 -684.05
 -684.01 -684.25 -684.24 -684.13 -684.43 -684.37 -684.49 -684.61  310.39  309.23
 -685.77 -685.86 -686.03 -687.22 -687.99 -688.67 -688.94 -689.41 -690.70 -691.01
 -691.43 -691.67 -692.43 -693.43 -694.20 -694.67 -695.10 -695.33 -695.70 -696.07
Pier Skew, UpSta & Num, DnSta & Num=  ,9954.18, 2 ,9927.27, 2 , 0 , 0 , 0 ,,
    4.00    4.00
 -685.12  314.88
    4.00    4.00
 -684.99  315.01
Pier Skew, UpSta & Num, DnSta & Num=  ,10040.27, 2 ,10013.36, 2 , 0 , 0 , 0 ,,
    4.00    4.00
 -685.51  314.49
    4.00    4.00
 -685.38  314.62
BR Coef=-1 , 0 , 0 ,, 0 ,,,0.8,0,1,0,
WSPro=,,,, 1 ,,,, 0 ,,,, 0 ,,,,-1 ,-1 ,-1 , 0 , 0 , 0 , 0 , 0
BC Design=,, 0 ,, 0 ,,,,,,

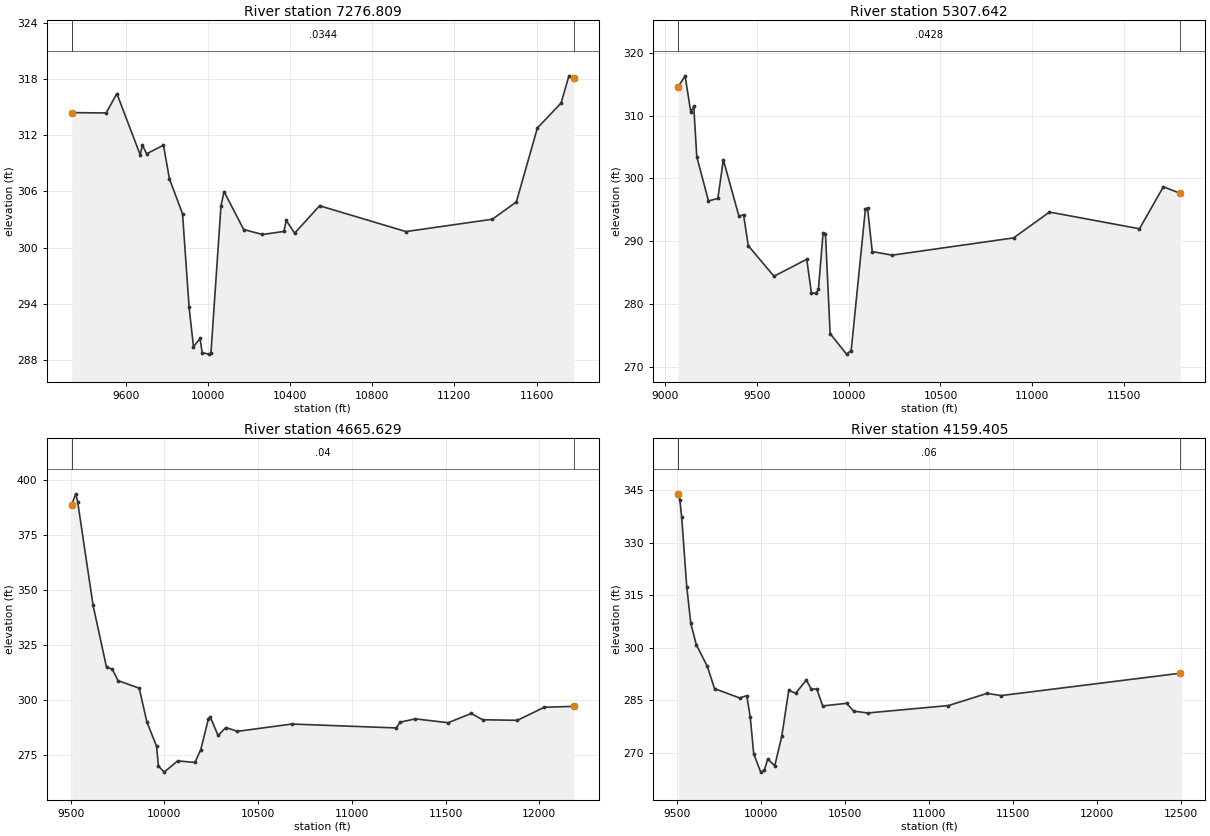
Type RM Length L Ch R = 1 ,7276.809,1969.166500,1969.166500,1969.166500
XS GIS Cut Line= 6
475784.722444504743829.246020228475286.462350726743963.620076641
474966.214952141744079.401696399474612.048285484744287.735029727
474229.800021589744624.410376951 473882.57779938745193.854821384
#Sta/Elev= 30
9337.507 314.4019505.045314.36499557.058316.43159670.861309.89269681.179310.9565
9701.815310.00739783.822310.93299813.087 307.3289876.761303.61229908.661293.6513
9929.928289.45119961.828290.32479972.462 288.81510004.36288.6562   10015288.7549
10063.88304.4545 10078.8305.9894 10174.5301.939810265.49301.412710369.91301.7323
10381.51302.918810422.47301.550510543.94304.472310964.34301.721311384.82303.0371
11501.95304.881711604.18312.765111719.43315.417811757.84 318.324 11781.7318.0487
#Mann= 3 , 0 , 0
9337.507  0.0344       09337.507  0.0344       0 11781.7  0.0344       0
#XS Ineff= 2 , 0
       09867.174        10117.84       0
Bank Sta=9337.507,11781.7
Exp/Cntr=0.3,0.1

Type RM Length L Ch R = 1 ,5307.642,642.013000,642.013000,642.013000
XS GIS Cut Line= 6
475634.313910574741532.599034354474556.188910544742402.188154727
474389.522243798742756.354821384474243.688910484743367.465932518
474239.181649417743618.545413777474215.911132693743693.854821399
#Sta/Elev= 30
9071.132314.58029108.493316.3204 9139.52310.55139155.649311.4779 9172.22303.4336
9235.946296.41559286.928296.8099 9316.94302.95249401.636293.99259427.126294.1903
9452.617 289.2939592.815284.4245 9771.25287.1282 9796.74281.76579822.231281.6966
9834.976282.37269860.467291.35549873.212291.19059898.703275.3018 9987.92272.0327
10013.41272.607310091.13295.178610102.63295.257710128.12288.352610236.29287.7818
10898.41290.529311093.74294.642111584.22291.982611714.24298.661411806.61 297.616
#Mann= 3 , 0 , 0
9071.132  0.0428       09071.132  0.0428       011806.61  0.0428       0
#XS Ineff= 2 , 0
       09786.479         10090.9       0
Bank Sta=9071.132,11806.61
Exp/Cntr=0.3,0.1

Type RM Length L Ch R = 1 ,4665.629,506.224200,506.224200,506.224200
XS GIS Cut Line= 4
474669.519160032741104.388274133 474504.58860442741824.874385238
474304.935826629742580.082718581474044.519159973 743708.55494079
#Sta/Elev= 30
9506.185388.7828 9527.33393.71149537.588390.14899619.658343.21049691.468315.0306
9722.244314.1841 9753.02308.94629865.866305.5241  9906.9290.22019958.194279.2233
9968.452270.20779999.228267.430310071.04272.522910163.37271.826810194.14277.5938
10235.18291.660710245.44292.363910286.81284.066610328.19287.668910390.25285.9349
10679.87289.252411236.76287.485211257.29290.093211339.39291.595611513.86289.8505
11637.01294.040211698.59291.184711883.32290.9538   12027296.873412184.59297.2679
#Mann= 3 , 0 , 0
9506.185    0.04       09506.185    0.04       012184.59    0.04       0
#XS Ineff= 2 , 0
       0 9942.55        10248.22       0
Bank Sta=9506.185,12184.59
Exp/Cntr=0.3,0.1

Type RM Length L Ch R = 1 ,4159.405,0.000000,0.000000,0.000000
XS GIS Cut Line= 5
474235.044397771741106.294670984474113.126960188741388.695266113
473993.769321382741792.341099441473554.935826629743222.443829641
473318.824715525743951.610496327
#Sta/Elev= 30
9505.573 343.9769515.055342.33279525.947337.45459556.145317.48299580.408306.9409
9613.084300.88039678.437294.69499722.005288.29039871.882285.63019913.594286.2857
 9934.45280.20819955.306269.63779997.018264.435210018.16264.913710038.73268.1973
10080.44266.247210122.15274.643310163.87287.775810205.58286.993210268.25290.7627
10298.07288.169710331.01288.191810366.25 283.34610508.84284.108610550.68 281.865
10634.36281.343311115.53283.464311345.65286.945311429.34286.313612496.45292.7054
#Mann= 3 , 0 , 0
9505.573    0.06       09505.573    0.06       012496.45    0.06       0
#XS Ineff= 2 , 0
       09876.165        10190.94       0
Bank Sta=9505.573,12496.45
Exp/Cntr=0.3,0.1